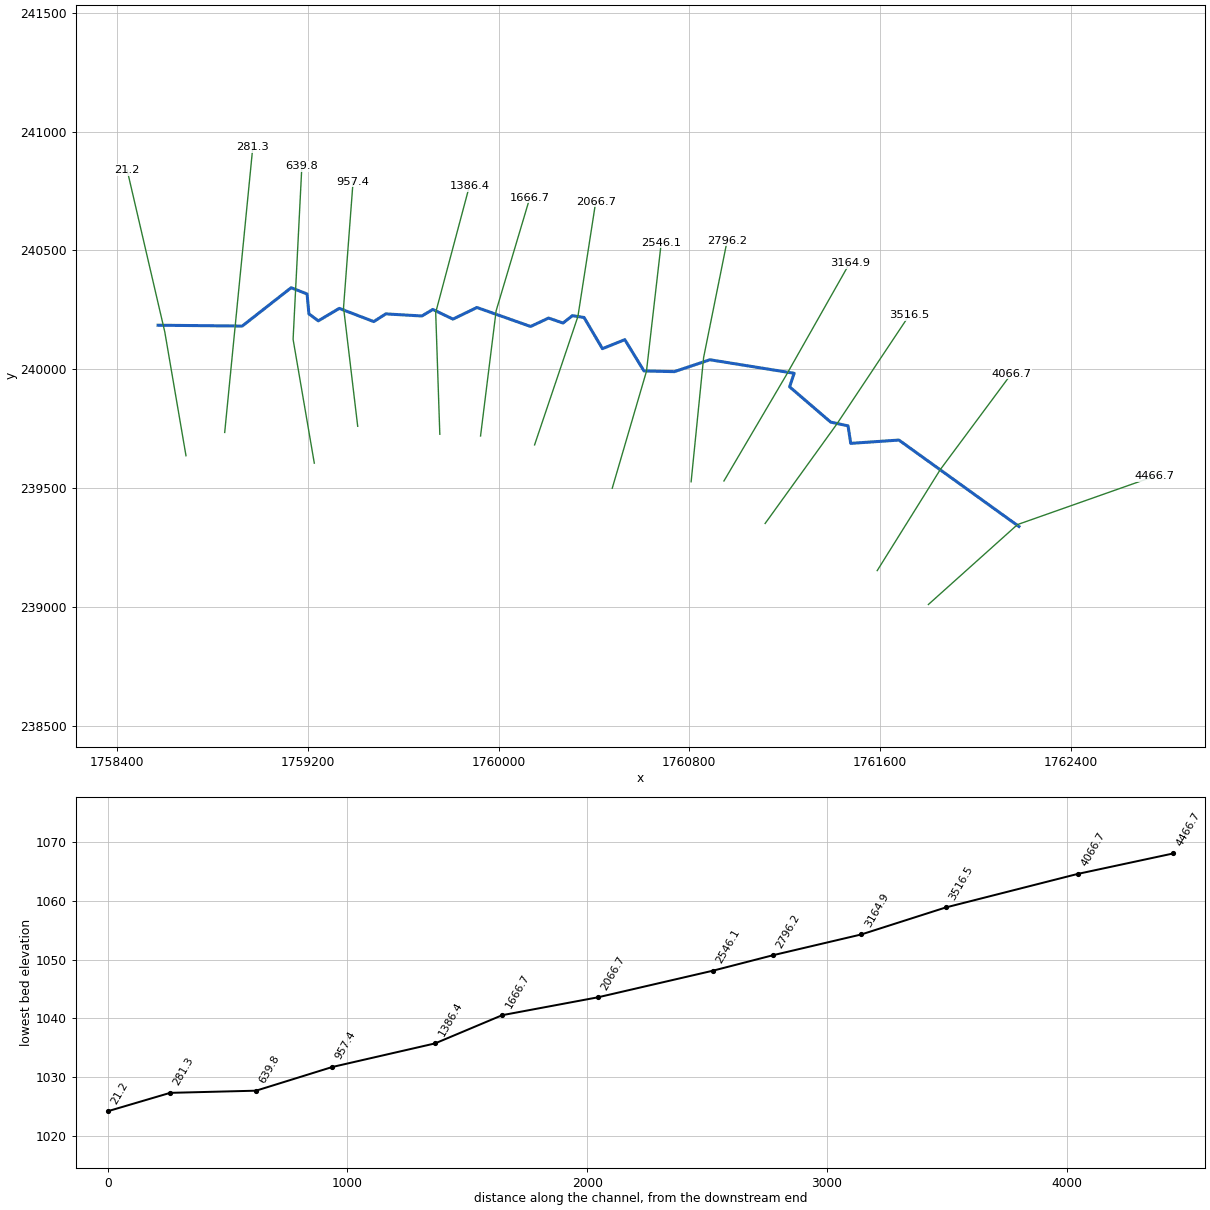
--- RaconCr.prj (project) ---

Proj Title=RaconCr
Current Plan=p01
Geom File=g01
Flow File=f01
Plan File=p01
DSS Export Rating Curves=0
DSS Export Rating Curve Sorted=0
DSS Export Volume Flow Curves=0
DXF OffsetX=0
DXF OffsetY=0
DXF ScaleX=0
DXF ScaleY=0

--- RaconCr.p01 (plan) ---

Plan Title=Floodplain
Program Version=4.00
Geom File=g01
Flow File=f01
K Sum by GR=0
Std Step Tol=0.01
Critical Tol=0.01
Num of Std Step Trials=20
Max Error Tol=0.3
Flow Tol Ratio=0.001
Split Flow NTrial=30
Split Flow Tol=0.02
Split Flow Ratio=0.02
Log Output Level=0
Friction Slope Method=1
Unsteady Friction Slope Method=2
Unsteady Bridges Friction Slope Method=1
Global Log Level=0
CheckData=False
Run HTab=0
Run UNet=0
Run PostProcess=0
UNET Theta=0
UNET Theta Warmup=0
UNET ZTol=0
UNET ZSATol=0
UNET MxIter=0
UNET MaxInSteps=0
UNET DtIC=0
UNET DtMin=0
UNET MaxCRTS=0
UNET WFStab=0
UNET SFStab=0
UNET WFX=0
UNET SFX=0
UNET DSS MLevel=0
UNET DZMax Abort=0
UNET Convert EG Bridges=0
UNET Use Existing IB Tables=0
UNET Froude Limit=0
UNET Froude Power=0
Write IC File=0
Echo Input=False
Echo Output=False
Write Detailed=0

--- RaconCr.f01 (steady flow) ---

Flow Title=NFF Regression Equation
Program Version=4.00
Number of Profiles=1
Profile Names=P100yr
River Rch & RM=RaconCr,Main      ,4466.7
768.1730
River Rch & RM=RaconCr,Main      ,3516.5
784.4978
River Rch & RM=RaconCr,Main      ,2066.7
870.4608
River Rch & RM=RaconCr,Main      ,957.4
929.4883
River Rch & RM=RaconCr,Main      ,639.8
929.4883
Boundary for River Rch & Prof#=RaconCr,Main      ,1
Up Type=0
Dn Type=3
Dn Slope=0.009499

--- RaconCr.g01 (geometry) ---

Geom Title=USGS 3m DEM
Program Version=4.00

River Reach=RaconCr     ,Main
Reach XY= 30
     1762183.491      239339.513     1761679.902      239702.827
     1761477.615      239688.965     1761466.388      239762.555
     1761393.612      239778.257     1761221.079      239926.737
     1761240.133      239983.569     1760886.707      240040.500
     1760737.499      239990.458     1760609.889      239993.566
     1760529.579      240125.049     1760435.683      240087.039
     1760358.545      240218.281     1760309.632      240225.863
     1760270.140      240194.811     1760209.729      240215.907
     1760134.254      240180.447     1759908.930      240260.240
     1759808.454      240211.378     1759723.897      240251.980
     1759678.093      240224.518     1759526.520      240233.379
     1759476.110      240201.005     1759331.192      240256.475
     1759243.300      240204.120     1759203.965      240233.296
     1759196.161      240317.238     1759129.341      240343.251
     1758923.996      240182.142     1758570.904      240185.741

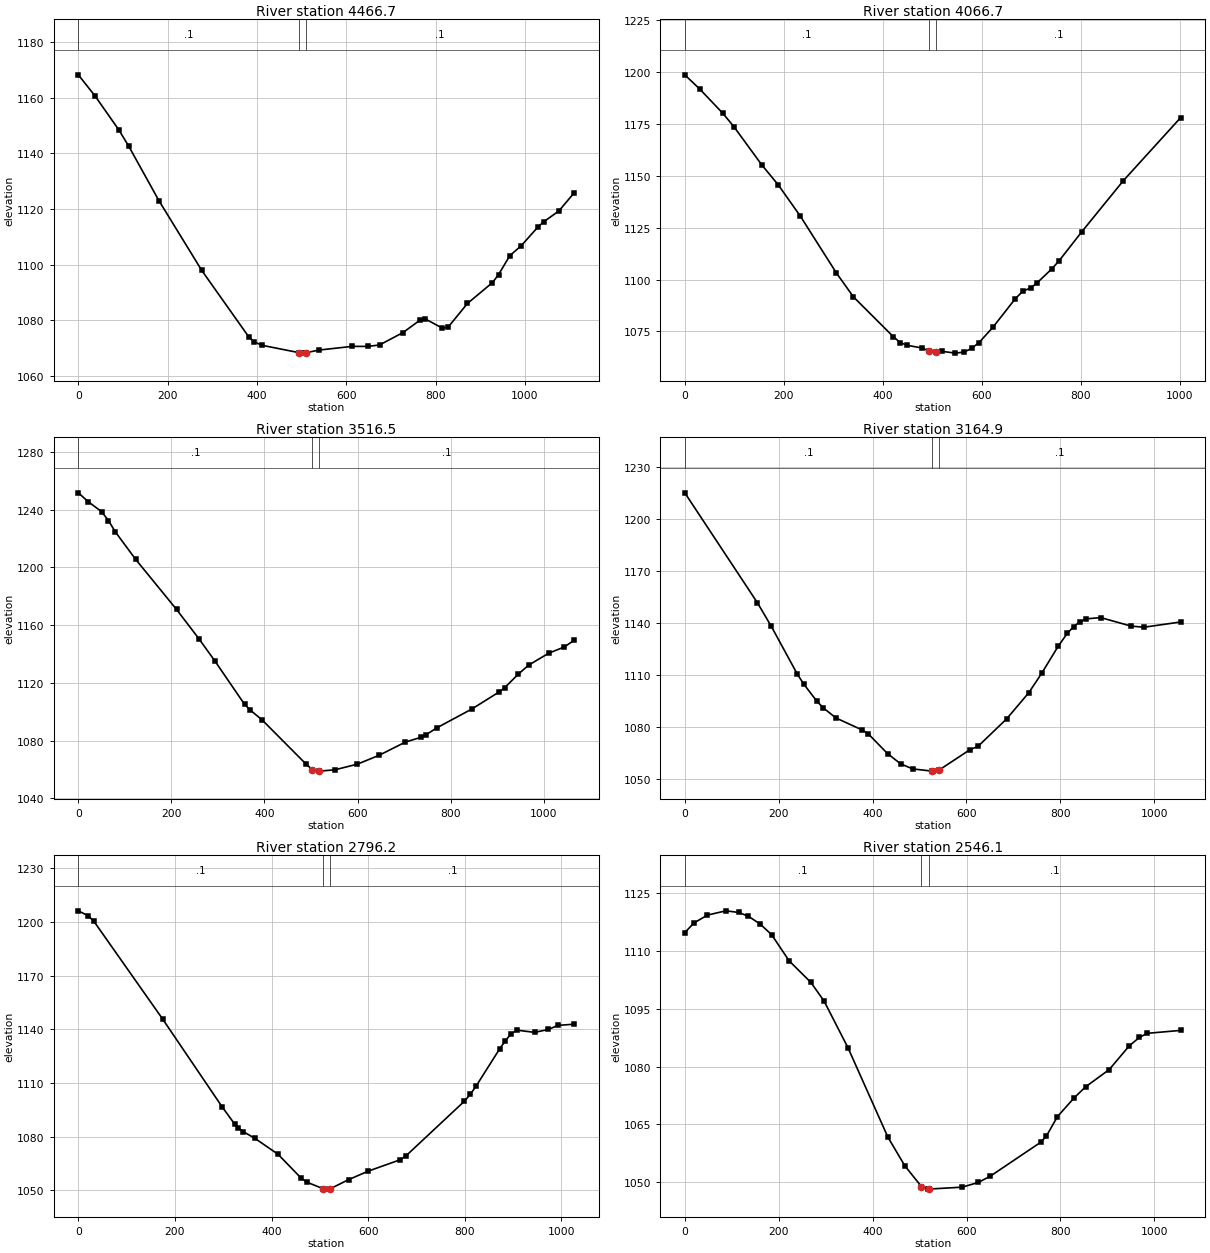
Type RM Length L Ch R = 1 ,4466.7,393.647,400,413.606
XS GIS Cut Line= 3
     1761803.586      239011.502     1762177.456      239347.487
     1762750.593      239550.013
#Sta/Elev= 30
       0 1168.33    37.8 1160.64    91.0 1148.43   113.0 1142.59   180.3 1123.06
   276.5 1097.86   382.1 1073.86   393.0 1072.25   410.8 1070.93   495.2 1068.23
   499.6 1068.09   510.2 1068.24   538.3 1069.18   613.8 1070.53   648.3 1070.50
   674.7 1071.03   727.2 1075.50   764.9 1079.94   777.5 1080.37   815.3 1077.09
   827.9 1077.39   871.6 1085.99   927.5 1093.49   941.2 1096.38   966.4 1103.20
   991.6 1106.72  1029.4 1113.51  1042.0 1115.36  1076.3 1119.30  1110.5 1125.83
#Mann= 3 , 0 , 0
       0     0.1       0   495.2   0.045       0   510.2     0.1       0
Bank Sta=   495.2,   510.2
Exp/Cntr=0.3,0.1

Type RM Length L Ch R = 1 ,4066.7,549.643,550.236,536.801
XS GIS Cut Line= 3
     1761588.765      239153.922     1761853.472      239578.697
     1762152.090      239981.758
#Sta/Elev= 30
       0 1198.50    29.8 1191.75    76.6 1180.05    99.1 1173.59   155.7 1155.13
   188.9 1145.54   233.8 1130.40   306.3 1103.19   340.8 1091.66   421.5 1072.49
   435.5 1069.64   449.5 1068.35   478.7 1067.10     493 1065.69     508 1065.34
   520.5 1065.43   546.9 1064.59   564.8 1065.12   579.6 1066.89   594.4 1069.60
   622.5 1076.97   668.2 1090.83   683.0 1094.34   699.7 1096.06   712.6 1098.54
   742.1 1105.21   756.9 1109.15   802.0 1122.88   886.4 1147.59  1002.1 1177.89
#Mann= 3 , 0 , 0
       0     0.1       0     493   0.045       0     508     0.1       0
Bank Sta=     493,     508
Exp/Cntr=0.3,0.1

Type RM Length L Ch R = 1 ,3516.5,343.85,351.628,349.974
XS GIS Cut Line= 3
     1761118.509      239352.185     1761420.191      239771.502
     1761723.932      240228.769
#Sta/Elev= 30
       0 1251.59    21.3 1245.44    50.2 1238.49    64.8 1232.35    79.4 1224.61
   122.9 1205.63   211.1 1170.81   259.0 1150.59   293.1 1135.32   357.3 1105.06
   369.6 1101.10   395.1 1094.29   488.3 1064.09   502.8 1059.88   517.8 1058.88
   551.2 1059.78   599.9 1063.73   646.5 1069.87   702.6 1078.95   736.9 1082.37
   746.2 1083.87   771.1 1088.98   846.0 1101.96   903.0 1113.45   915.9 1116.54
   945.8 1126.16   968.1 1132.37  1010.9 1140.54  1044.7 1144.90  1065.5 1149.53
#Mann= 3 , 0 , 0
       0     0.1       0   502.8   0.045       0   517.8     0.1       0
Bank Sta=   502.8,   517.8
Exp/Cntr=0.3,0.1

Type RM Length L Ch R = 1 ,3164.9,359.465,368.646,376.673
XS GIS Cut Line= 3
     1760945.576      239530.808     1761205.865      239973.820
     1761472.857      240446.336
#Sta/Elev= 30
       0 1215.29   154.4 1151.83   184.3 1138.06   239.4 1110.59   253.2 1104.73
   280.7 1094.99   294.5 1091.01   322.0 1085.05   377.1 1078.21   390.9 1075.86
   432.2 1064.39   459.7 1058.55   485.5 1055.57   526.6 1054.31   528.4 1054.29
   541.6 1054.87   607.4 1066.66   624.8 1068.62   685.8 1084.53   733.0 1099.66
   760.3 1110.81   795.3 1126.41   814.8 1133.92   828.5 1137.89   842.1 1140.73
   855.7 1142.38   886.2 1143.11   951.2 1138.18   978.5 1137.54  1056.5 1140.57
#Mann= 3 , 0 , 0
       0     0.1       0   526.6   0.045       0   541.6     0.1       0
Bank Sta=   526.6,   541.6
Exp/Cntr=0.3,0.1

Type RM Length L Ch R = 1 ,2796.2,254.239,250.138,250.876
XS GIS Cut Line= 3
     1760807.892      239527.535     1760860.347      240050.265
     1760959.203      240541.742
#Sta/Elev= 30
       0 1206.26    20.0 1203.54    31.8 1200.56   174.9 1145.66   298.1 1096.59
   323.7 1087.10   330.1 1085.16   342.0 1082.80   365.9 1079.08   413.6 1070.21
   461.3 1056.91   473.3 1054.64   507.1 1050.95   509.1 1050.75   522.1 1051.02
   559.6 1056.05   600.0 1060.77   666.2 1067.14   678.4 1069.33   799.5 1099.90
   811.6 1103.71   823.7 1108.34   872.5 1129.16   884.2 1133.63   896.3 1137.61
   908.5 1139.57   944.8 1138.34   973.0 1139.95   993.3 1142.25  1026.7 1142.91
#Mann= 3 , 0 , 0
       0     0.1       0   507.1   0.045       0   522.1     0.1       0
Bank Sta=   507.1,   522.1
Exp/Cntr=0.3,0.1

Type RM Length L Ch R = 1 ,2546.1,481.759,479.351,475.525
XS GIS Cut Line= 3
     1760476.844      239500.238     1760620.419      239991.854
     1760682.433      240531.938
#Sta/Elev= 30
       0 1114.81    19.4 1117.31    48.1 1119.37    87.6 1120.48   115.1 1120.05
   135.6 1119.05   160.3 1117.06   185.0 1114.26   222.2 1107.47   268.3 1101.89
   296.4 1097.06   347.6 1084.85   432.4 1061.65   468.7 1054.15     504 1048.79
   518.8 1048.12     519 1048.13   590.5 1048.63   625.0 1049.86   650.2 1051.46
   757.8 1060.30   769.7 1061.86   793.6 1066.99   829.5 1071.91   853.4 1074.71
   903.7 1079.20   946.6 1085.39   968.0 1087.57   984.8 1088.63  1055.8 1089.39
#Mann= 3 , 0 , 0
       0     0.1       0     504   0.045       0     519     0.1       0
Bank Sta=     504,     519
Exp/Cntr=0.3,0.1

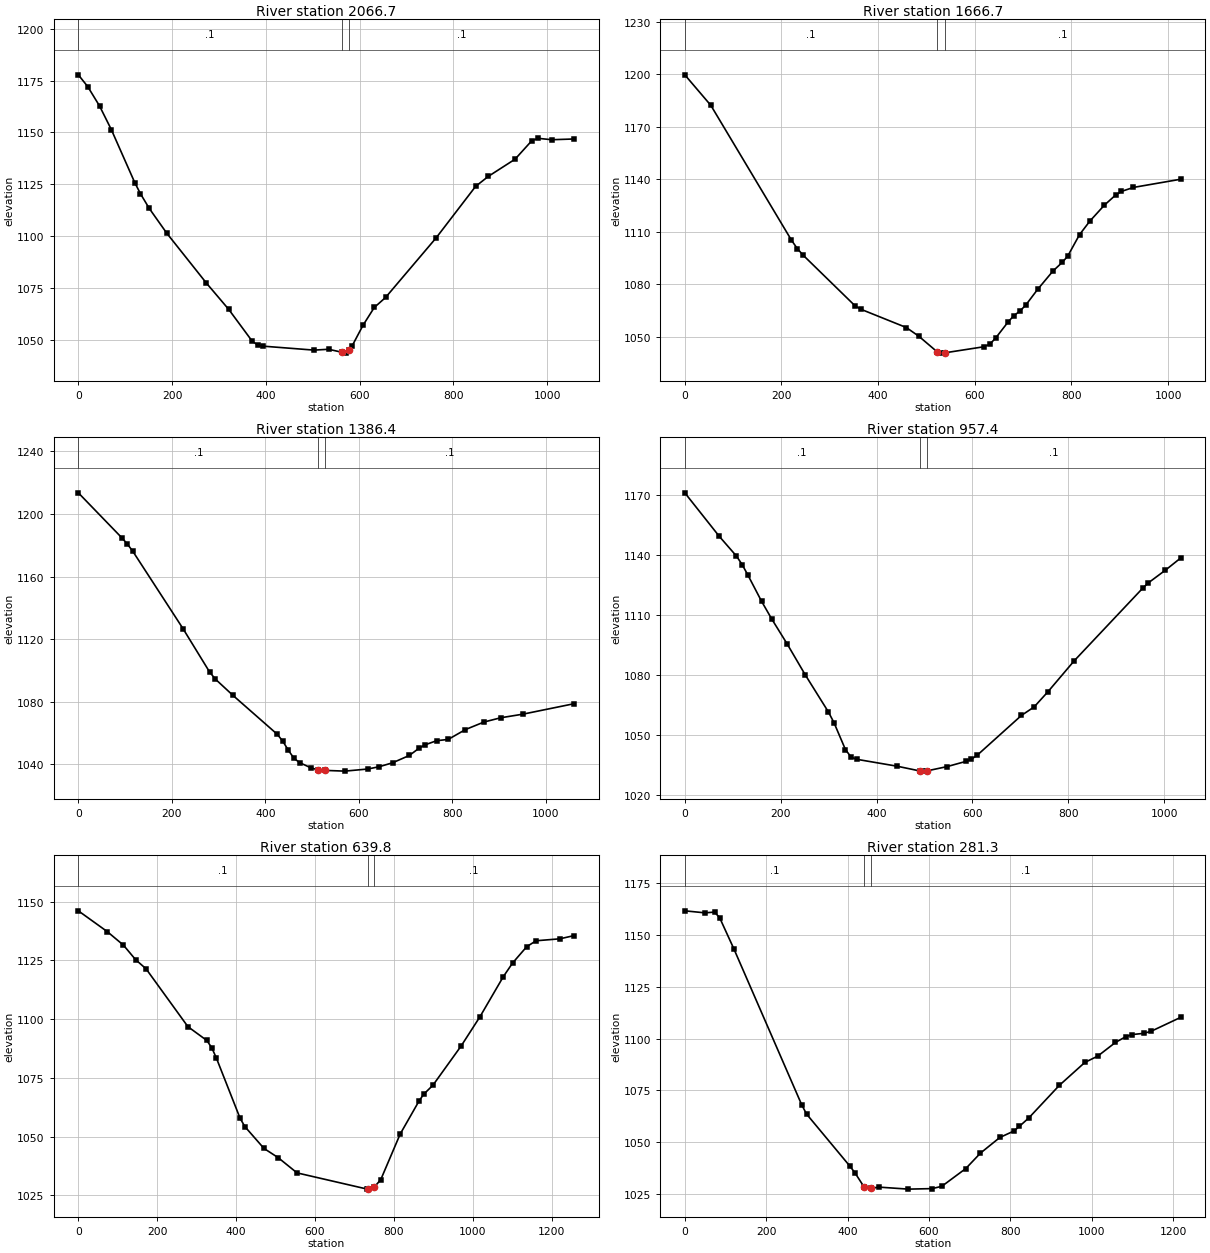
Type RM Length L Ch R = 1 ,2066.7,393.615,400,395.479
XS GIS Cut Line= 3
     1760150.910      239682.459     1760332.740      240222.281
     1760407.539      240704.820
#Sta/Elev= 30
       0 1177.77    20.0 1172.11    45.3 1162.74    70.3 1151.41   120.4 1125.81
   132.4 1120.50   151.2 1113.40   188.7 1101.41   273.0 1077.43   320.9 1064.67
   371.0 1049.34   383.5 1047.38   394.8 1046.94   502.9 1045.04   533.9 1045.45
   562.1 1044.03   571.4 1043.59   577.1 1045.00   583.7 1046.87   607.4 1057.01
   631.4 1065.59   655.5 1070.42   763.6 1099.21   847.7 1124.00   874.9 1128.83
   931.8 1137.09   967.8 1146.07   981.1 1147.15  1010.1 1146.48  1057.9 1146.84
#Mann= 3 , 0 , 0
       0     0.1       0   562.1   0.045       0   577.1     0.1       0
Bank Sta=   562.1,   577.1
Exp/Cntr=0.3,0.1

Type RM Length L Ch R = 1 ,1666.7,274.462,280.299,282.88
XS GIS Cut Line= 3
     1759924.183      239720.032     1759989.537      240246.074
     1760130.907      240721.216
#Sta/Elev= 30
       0 1199.71    53.9 1182.23   220.7 1105.13   232.7 1100.34   244.6 1096.62
   352.3 1067.58   364.3 1065.63   458.3 1055.18   483.9 1050.26   522.6 1041.17
   531.8 1040.54   537.6 1040.70   618.0 1044.15   630.9 1045.60   643.3 1049.23
   668.1 1058.09   680.5 1061.92   692.9 1064.49   705.3 1067.98   730.0 1077.01
   761.6 1087.46   780.7 1092.41   792.0 1095.92   816.7 1108.33   838.0 1116.04
   867.8 1125.09   891.1 1130.91   903.4 1133.04   928.2 1135.31  1025.8 1139.99
#Mann= 3 , 0 , 0
       0     0.1       0   522.6   0.045       0   537.6     0.1       0
Bank Sta=   522.6,   537.6
Exp/Cntr=0.3,0.1

Type RM Length L Ch R = 1 ,1386.4,428.426,429.048,431.463
XS GIS Cut Line= 3
     1759753.273      239727.303     1759735.958      240239.197
     1759876.966      240769.386
#Sta/Elev= 30
       0 1213.46    93.1 1184.73   105.0 1180.72   116.8 1176.00   223.8 1126.80
   280.9 1099.01   293.2 1094.49   330.7 1084.13   425.7 1059.23   437.6 1054.77
   449.5 1048.96   461.3 1043.96   473.2 1041.20   497.0 1037.91   513.5 1036.43
   528.5 1036.19   570.2 1035.73   619.3 1037.08   643.9 1038.56   672.5 1041.08
   708.1 1045.73   729.9 1050.57   742.2 1052.56   766.4 1055.15   791.3 1055.98
   828.2 1062.27   867.8 1067.08   903.4 1069.79   951.0 1072.10  1060.8 1078.80
#Mann= 3 , 0 , 0
       0     0.1       0   513.5   0.045       0   528.5     0.1       0
Bank Sta=   513.5,   528.5
Exp/Cntr=0.3,0.1

Type RM Length L Ch R = 1 ,957.4,321.604,317.624,316.289
XS GIS Cut Line= 3
     1759408.636      239760.799     1759349.248      240260.274
     1759389.217      240789.851
#Sta/Elev= 30
       0 1170.90    71.9 1149.13   107.8 1139.25   119.7 1134.97   131.7 1129.72
   160.0 1116.69   181.4 1107.76   213.5 1095.32   251.3 1079.83   299.3 1061.39
   311.0 1056.03   335.0 1042.50   346.9 1038.71   358.9 1037.61   442.6 1034.18
   489.8 1031.82   502.0 1031.71   504.8 1031.82   547.1 1033.98   585.7 1036.54
   597.6 1037.69   609.5 1039.59   702.1 1059.57   728.6 1063.82   757.5 1071.45
   811.9 1086.82   954.8 1123.15   966.7 1125.86  1002.4 1132.22  1034.1 1138.28
#Mann= 3 , 0 , 0
       0     0.1       0   489.8   0.045       0   504.8     0.1       0
Bank Sta=   489.8,   504.8
Exp/Cntr=0.3,0.1

Type RM Length L Ch R = 1 ,639.8,357.333,358.429,359.524
XS GIS Cut Line= 3
     1759226.523      239605.806     1759137.524      240126.449
     1759174.335      240854.657
#Sta/Elev= 30
       0 1146.11    73.1 1137.30   114.3 1131.52   145.4 1125.30   171.7 1121.44
   277.9 1096.81   325.7 1090.96   338.1 1087.92   350.1 1083.44   410.4 1057.74
   422.4 1054.27   470.6 1045.02   506.7 1041.08   554.6 1034.59   732.8 1027.68
   734.7 1027.69   749.7 1028.41   766.9 1031.72   816.1 1051.11   863.6 1065.08
   875.5 1068.02   899.3 1071.92   970.6 1088.57  1018.2 1100.97  1077.6 1118.08
  1101.4 1123.95  1137.1 1130.87  1160.8 1133.37  1221.1 1134.20  1257.3 1135.58
#Mann= 3 , 0 , 0
       0     0.1       0   734.7   0.045       0   749.7     0.1       0
Bank Sta=   734.7,   749.7
Exp/Cntr=0.3,0.1

Type RM Length L Ch R = 1 ,281.3,255.017,260.149,265.28
XS GIS Cut Line= 2
     1758850.503      239734.854     1758968.426      240934.113
#Sta/Elev= 30
       0 1161.64    49.3 1160.67    73.0 1161.02    85.5 1158.37   120.5 1143.32
   287.3 1068.01   299.2 1063.54   405.5 1038.44   417.9 1035.25   441.4 1028.10
   456.4 1027.79   477.9 1028.27   549.1 1027.31   607.9 1027.56   631.6 1028.68
   690.4 1037.23   726.6 1044.71   774.1 1052.23   809.1 1055.40   822.2 1057.62
   845.5 1061.71   920.4 1077.41   983.0 1088.46  1014.8 1091.52  1058.1 1098.09
  1083.1 1100.84  1099.3 1101.92  1127.4 1102.49  1145.7 1103.48  1218.4 1110.21
#Mann= 3 , 0 , 0
       0     0.1       0   441.4   0.045       0   456.4     0.1       0
Bank Sta=   441.4,   456.4
Exp/Cntr=0.3,0.1

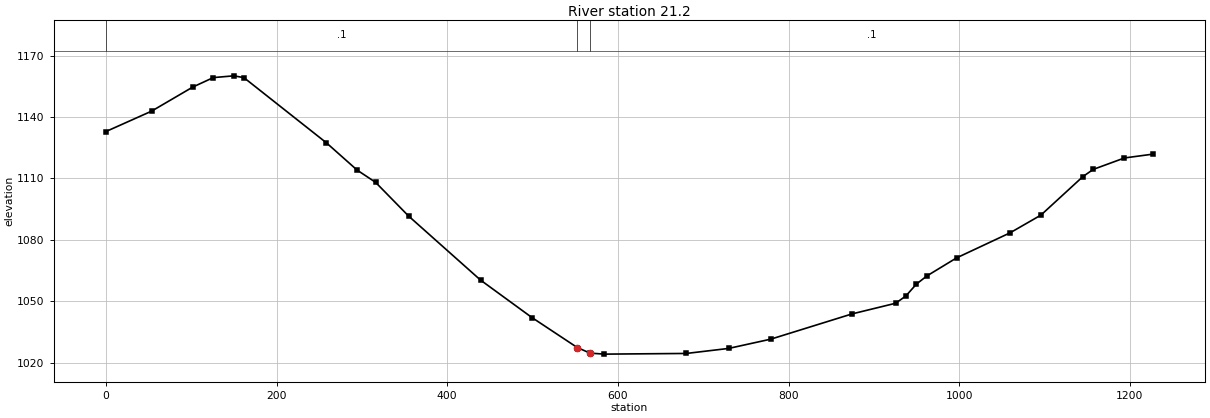
Type RM Length L Ch R = 1 ,21.2,23.4,21.189,18.978
XS GIS Cut Line= 3
     1758688.080      239636.955     1758599.081      240157.598
     1758441.108      240838.439
#Sta/Elev= 30
       0 1132.88    53.5 1142.84   101.7 1154.59   125.8 1159.23   149.9 1160.10
   161.7 1159.22   258.3 1127.42   294.4 1114.06   316.0 1108.09   354.7 1091.62
   439.0 1060.35   499.2 1042.06   552.4 1027.39   567.4 1024.66   584.2 1024.18
   680.2 1024.51   729.7 1026.96   779.2 1031.50   874.5 1043.84   925.4 1049.02
   937.4 1052.57   949.8 1058.39   962.0 1062.35   996.8 1071.17  1059.5 1083.41
  1095.7 1092.08  1144.8 1110.86  1157.0 1114.40  1193.6 1119.99  1227.1 1121.86
#Mann= 3 , 0 , 0
       0     0.1       0   552.4   0.045       0   567.4     0.1       0
Bank Sta=   552.4,   567.4
Exp/Cntr=0.3,0.1